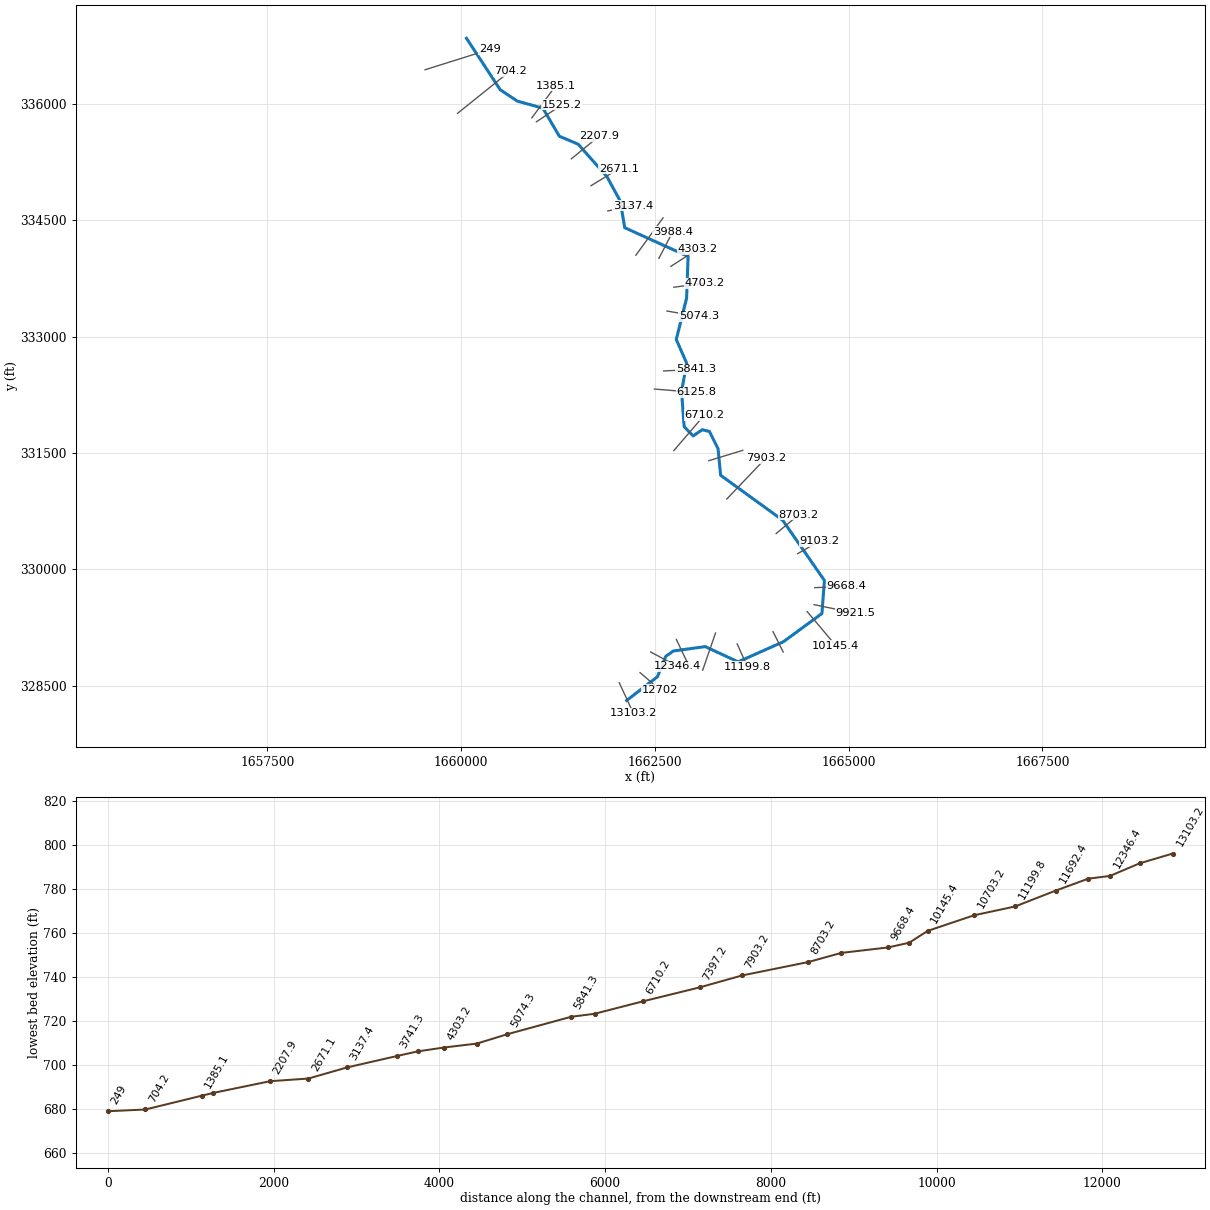
--- CRAWLEYCRK.prj (project) ---

Proj Title=CRAWLEYCRK
Current Plan=p01
Default Exp/Contr=0,0
English Units
Geom File=g01
Flow File=f01
Plan File=p01
BEGIN DESCRIPTION:
END DESCRIPTION:
DSS Export Rating Curves= 0
DSS Export Rating Curve Sorted= 0
DSS Export Volume Flow Curves= 0
DXF OffsetX= 0
DXF OffsetY= 0
DXF ScaleX= 0
DXF ScaleY= 0

--- CRAWLEYCRK.p01 (plan) ---

Plan Title=Floodplain
Program Version=4.00
Geom File=g01
Flow File=f01
K Sum by GR=0
Std Step Tol=0.01
Critical Tol=0.01
Num of Std Step Trials=20
Max Error Tol=0.3
Flow Tol Ratio=0.001
Split Flow NTrial=30
Split Flow Tol=0.02
Split Flow Ratio=0.02
Log Output Level=0
Friction Slope Method=1
Unsteady Friction Slope Method=2
Unsteady Bridges Friction Slope Method=1
Global Log Level=0
CheckData=False
Run HTab=0
Run UNet=0
Run PostProcess=0
UNET Theta=0
UNET Theta Warmup=0
UNET ZTol=0
UNET ZSATol=0
UNET MxIter=0
UNET MaxInSteps=0
UNET DtIC=0
UNET DtMin=0
UNET MaxCRTS=0
UNET WFStab=0
UNET SFStab=0
UNET WFX=0
UNET SFX=0
UNET DSS MLevel=0
UNET DZMax Abort=0
UNET Convert EG Bridges=0
UNET Use Existing IB Tables=0
UNET Froude Limit=0
UNET Froude Power=0
Write IC File=0
Echo Input=False
Echo Output=False
Write Detailed=0

--- CRAWLEYCRK.f01 (steady flow) ---

Flow Title=NFF Regression Equation
Program Version=4.00
Number of Profiles= 1
Profile Names=P100yr
River Rch & RM=CRAWLEYCRK,Main            ,13103.2
827.7684
River Rch & RM=CRAWLEYCRK,Main            ,12702
 1044.03
River Rch & RM=CRAWLEYCRK,Main            ,10145.4
 1104.15
River Rch & RM=CRAWLEYCRK,Main            ,9668.4
1587.492
River Rch & RM=CRAWLEYCRK,Main            ,6125.8
1703.109
River Rch & RM=CRAWLEYCRK,Main            ,704.2
1861.405
River Rch & RM=CRAWLEYCRK,Main            ,249
2122.911
Boundary for River Rch & Prof#=CRAWLEYCRK,Main            , 1
Up Type= 0
Dn Type= 1
Dn Known WS=691.31
DSS Import GetInterval= 0
DSS Import GetPeak= 0
DSS Import FillOption= 0

--- CRAWLEYCRK.g01 (geometry) ---

Geom Title=USGS 10m DEM
Program Version=4.10

River Reach=CRAWLEYCRK      ,Main
Reach XY= 30
     1662136.682      328310.099     1662532.876      328615.193
     1662640.612      328879.319      1662739.08      328947.668
     1663149.171      329004.432     1663574.322      328807.495
     1664158.181      329066.988     1664655.156      329430.741
     1664687.593      329857.051     1664147.755      330635.529
     1663348.424      331213.596      1663314.83      331556.497
     1663203.618      331778.919     1663110.942       331800.93
     1662993.939      331720.997     1662878.094      331840.317
     1662844.499      332293.271     1662910.531      332659.341
      1662776.15      332964.014     1662909.372      333498.059
     1662929.066       334035.58       1662111.2      334406.284
     1662054.436      334748.026     1661881.827      335064.283
     1661511.123      335482.484     1661267.849      335585.585
     1661055.852      335947.022     1660725.694       336038.54
     1660505.589      336184.504     1660070.011      336848.296

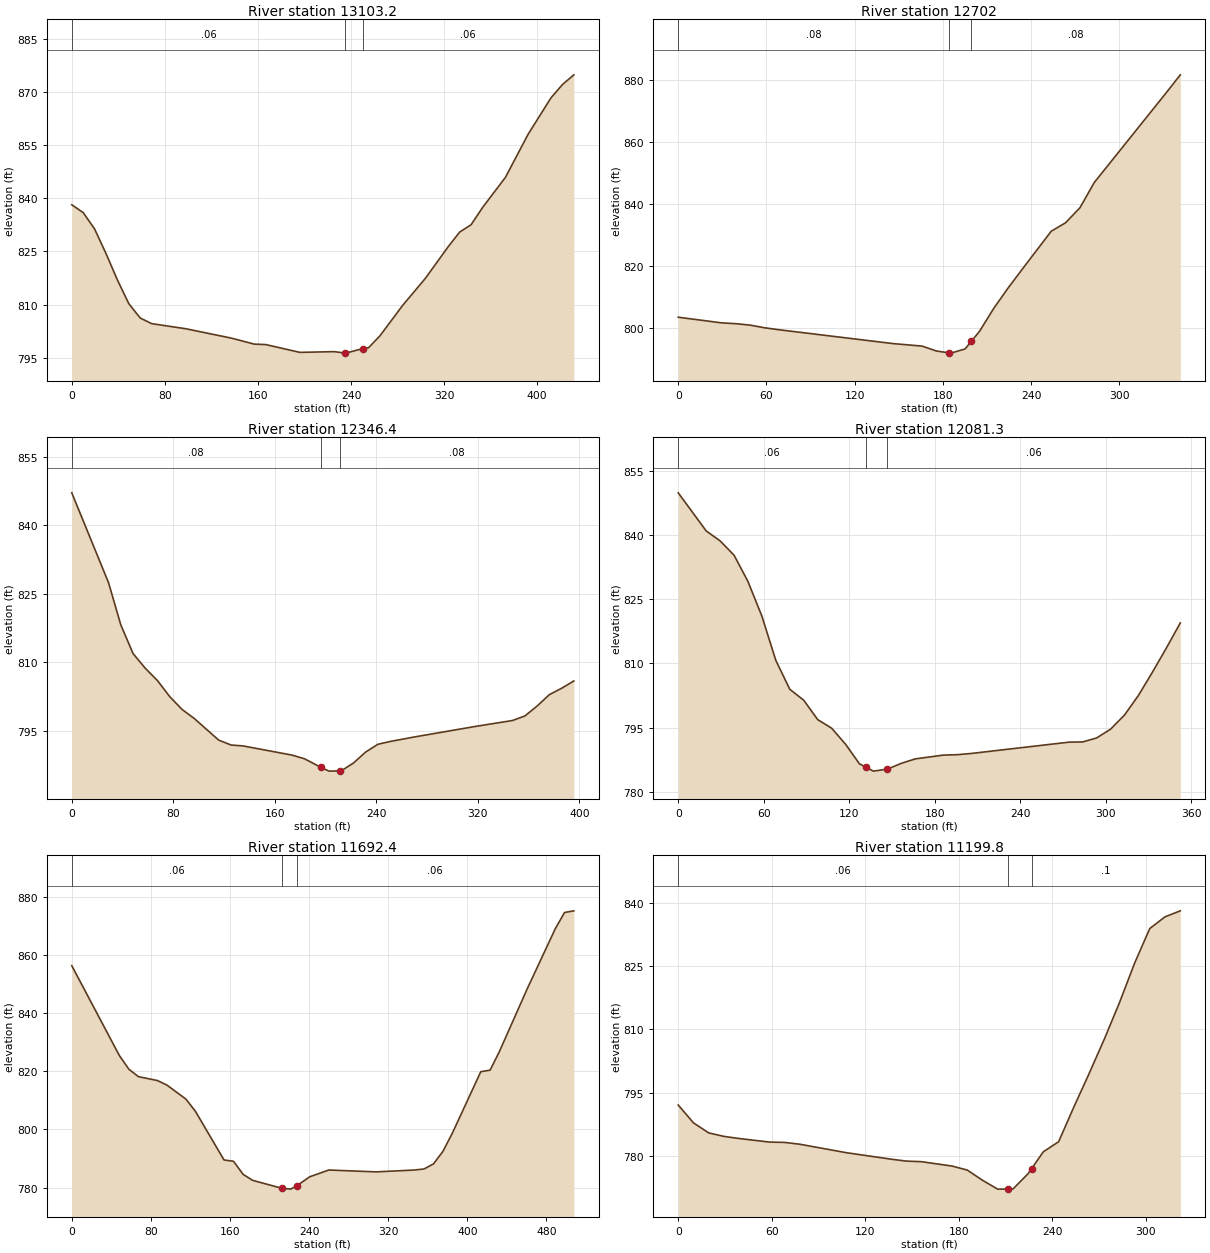
Type RM Length L Ch R = 1 ,13103.2 ,390.9,401.2,411.4
XS GIS Cut Line= 2
     1662041.112      328537.888     1662222.335       328146.27
#Sta/Elev= 30
       0   838.2     9.8  835.99    19.6  831.38    29.4  824.44    39.2  816.99
      49  810.28    58.8  806.23    68.6  804.63    98.1  803.18   137.3  800.53
   156.9  798.84   166.7  798.72   196.1  796.51   225.6  796.72   234.9  796.32
   235.4   796.3   249.9  797.56     255  797.81   264.8  801.16   284.4  809.79
     304  817.46   323.6  826.39   333.4  830.49   343.2  832.56   353.1  837.44
   372.7  845.93   392.3  858.16   411.9  868.41   421.7  872.14   431.5  874.89
#Mann= 3 , 0 , 0
       0     .06       0   234.9    .045       0   249.9     .06       0
Bank Sta=234.9,249.9
XS Rating Curve= 0 ,0
Exp/Cntr=0.3,0.1

Type RM Length L Ch R = 1 ,12702   ,350.8,355.4,360.1
XS GIS Cut Line= 2
     1662308.563      328669.194     1662567.172      328446.263
#Sta/Elev= 23
       0   803.4    29.3  801.59      39  801.32    48.8  800.86    58.5  800.01
    68.3  799.37   146.3  794.88   165.8  794.09   175.6   792.5   184.4  791.89
   185.4  791.82   195.1  793.18   199.4  795.68   204.9  798.87   214.6   806.3
   224.4  812.88   234.1  818.99   253.6  831.12   263.4  833.86   273.2  838.73
   282.9  846.84   331.7  875.71   341.4  881.56
#Mann= 3 , 0 , 0
       0     .08       0   184.4    .045       0   199.4     .08       0
Bank Sta=184.4,199.4
XS Rating Curve= 0 ,0
Exp/Cntr=0.3,0.1

Type RM Length L Ch R = 1 ,12346.4 ,279.4,265.2,250.9
XS GIS Cut Line= 2
     1662445.663      328935.021     1662794.643      328748.487
#Sta/Elev= 30
       0  847.13      29  827.42    38.6  818.22    48.3  811.89    57.9  808.68
    67.6  805.95    77.2  802.45    86.9  799.64    96.5  797.66   115.8  792.91
   125.5  791.84   135.1  791.63   173.7  789.62   183.4  788.82   196.3  786.95
   202.7  786.11   211.3  786.16   212.3  786.17     222  787.88   231.6  790.29
   241.3     792   250.9  792.61   270.2  793.61   318.5  795.93   347.4  797.21
   357.1   798.2   366.8  800.39   376.4  802.88     386  804.27   395.7  805.88
#Mann= 3 , 0 , 0
       0     .08       0   196.3    .045       0   211.3     .08       0
Bank Sta=196.3,211.3
XS Rating Curve= 0 ,0
Exp/Cntr=0.3,0.1

Type RM Length L Ch R = 1 ,12081.3 ,406.4,388.9,371.3
XS GIS Cut Line= 2
     1662777.446      329096.157      1662929.14      328778.107
#Sta/Elev= 30
       0  849.82    19.6  840.93    29.4   838.6    39.2  835.25    48.9  829.14
    58.7  821.04    68.5  810.69    78.3  803.94    88.1  801.38    97.9  796.85
   107.7  794.84   117.5  791.08   127.2  786.52   131.8  785.72     137  784.82
   146.8  785.29   156.6  786.64   166.4  787.68     186  788.56   195.8  788.66
   205.6  788.94   274.1  791.58   283.9  791.64   293.6  792.56   303.4   794.6
   313.2  797.91     323  802.49   332.8  807.91   342.6  813.56   352.4  819.44
#Mann= 3 , 0 , 0
       0     .06       0   131.8    .045       0   146.8     .06       0
Bank Sta=131.8,146.8
XS Rating Curve= 0 ,0
Exp/Cntr=0.3,0.1

Type RM Length L Ch R = 1 ,11692.4 ,475.5,492.6,509.6
XS GIS Cut Line= 3
      1663282.65      329179.611     1663150.448      328797.551
     1663116.608      328699.755
#Sta/Elev= 30
       0   856.4    48.1  825.46    57.8  820.72    67.4  818.18    86.6  816.84
    96.3  815.26   115.5  810.43   125.1  806.22     154  789.48   163.6  789.03
   173.3  784.53   182.9  782.47   212.4  779.74   221.4  779.44   227.4  780.55
   240.6  783.68   259.9  786.02     308  785.38   346.5  786.02   356.2  786.37
   365.8  788.11   375.4  792.45     385  798.77   413.7  819.89   423.1   820.4
   432.5  826.81   460.7  848.46     489  869.09   498.4  874.71   507.8  875.28
#Mann= 3 , 0 , 0
       0     .06       0   212.4    .045       0   227.4     .06       0
Bank Sta=212.4,227.4
XS Rating Curve= 0 ,0
Exp/Cntr=0.3,0.1

Type RM Length L Ch R = 1 ,11199.8 ,495.5,496.5,497.4
XS GIS Cut Line= 2
     1663561.912      329039.094     1663693.787      328745.165
#Sta/Elev= 30
       0  792.08     9.8  787.86    19.5  785.49    29.3  784.66      39  784.16
    58.6  783.31    68.3  783.23    78.1   782.8   107.4  780.83   136.7  779.26
   146.4  778.81   156.2  778.67   175.7  777.64   185.5  776.69   195.2  774.29
     205  772.18   211.8   772.2   214.8  772.21   224.5  775.82   226.8  777.04
   234.3  781.02   244.1  783.39   253.8  791.54   263.6  799.46   273.4  807.64
   283.1  816.25   292.9  825.67   302.6  833.84   312.4  836.61   322.2  838.03
#Mann= 3 , 0 , 0
       0     .06       0   211.8    .045       0   226.8      .1       0
Bank Sta=211.8,226.8
XS Rating Curve= 0 ,0
Exp/Cntr=0.3,0.1

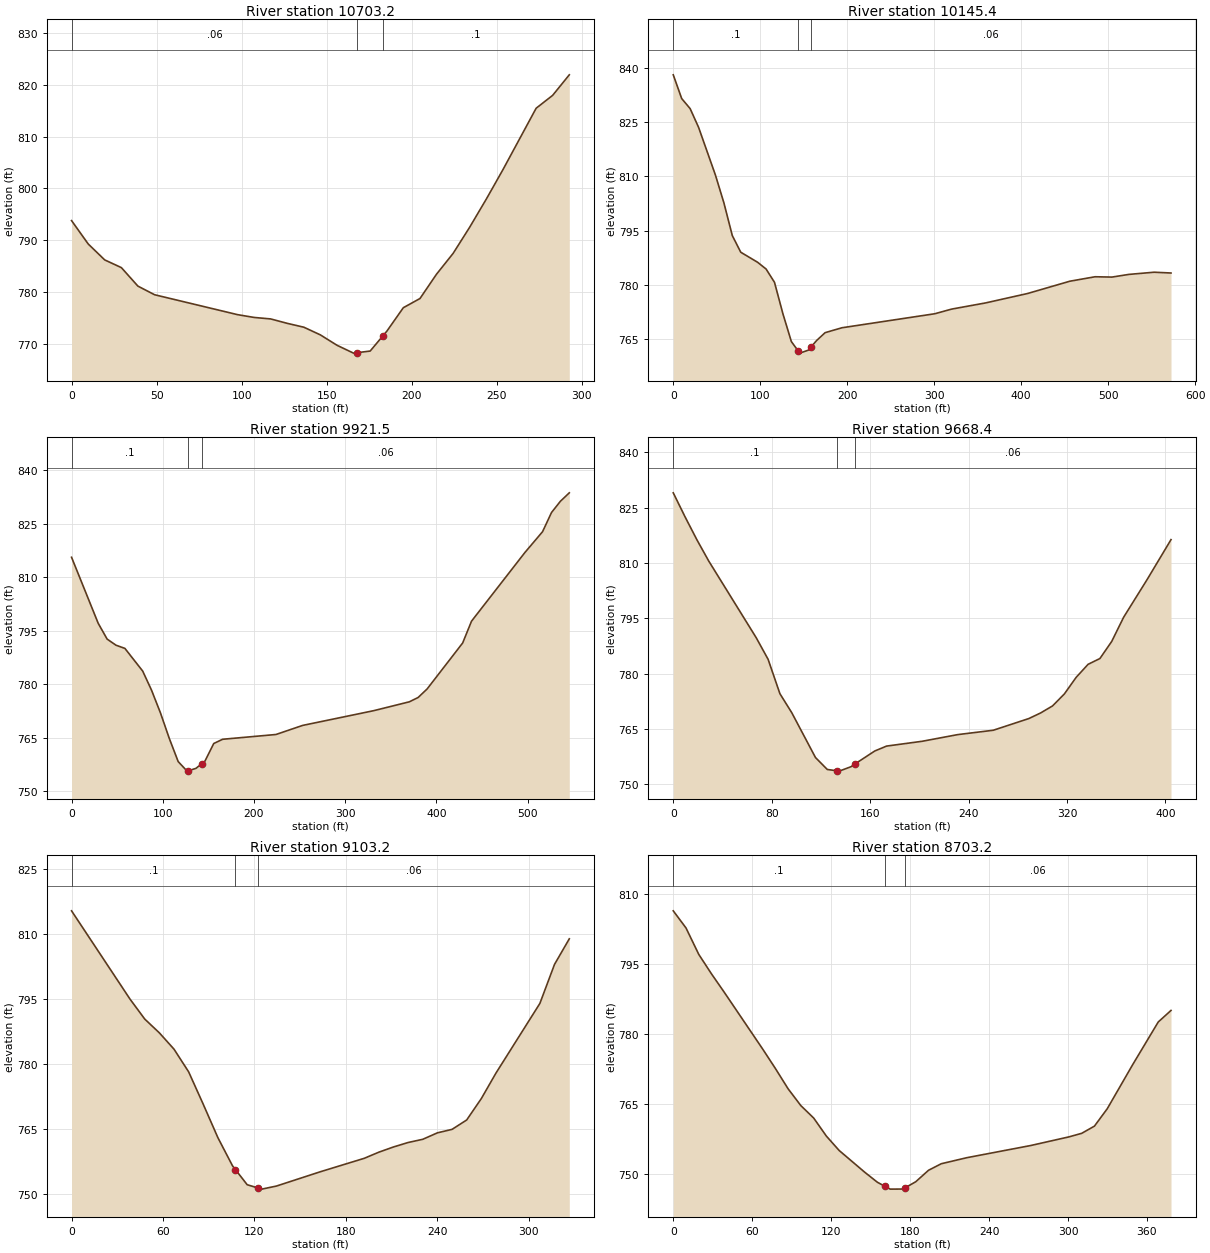
Type RM Length L Ch R = 1 ,10703.2 ,552.8,557.8,562.8
XS GIS Cut Line= 2
     1664024.639      329196.483      1664155.53      328934.702
#Sta/Elev= 28
       0  793.78     9.8  789.26    19.5  786.18    29.3  784.69      39  781.12
    48.8  779.45    97.6   775.6   107.3  775.06   117.1  774.77   126.8  773.92
   136.6  773.17   146.3  771.69   156.1  769.68   165.8  768.16     168  768.25
   175.6  768.56     183  771.46   185.4   772.4   195.1  776.94   204.9  778.72
   214.6  783.41   224.4  787.45   234.1  792.49   243.9  797.94   253.7  803.64
   273.2   815.5   282.9  817.99   292.7  821.96
#Mann= 3 , 0 , 0
       0     .06       0     168    .045       0     183      .1       0
Bank Sta=168,183
XS Rating Curve= 0 ,0
Exp/Cntr=0.3,0.1

Type RM Length L Ch R = 1 ,10145.4 ,208.8,223.9,239
XS GIS Cut Line= 2
     1664464.992       329455.61     1664834.106      329018.219
#Sta/Elev= 30
       0  838.17     9.7  831.59    19.4  828.81    29.1  823.63    48.5  810.39
    58.2  802.72    67.9  793.62    77.6  789.02      97  786.23   106.7  784.37
   116.4  780.68   126.1  771.95   135.8  764.26   143.5  761.72   145.5  761.06
   155.2  761.87   158.5  762.79   164.9  764.57   174.6  766.73     194  768.09
   300.7  771.97   320.1  773.26   358.9  774.96   407.4  777.58   455.9  780.98
     485  782.22   504.4  782.13   523.8  782.87   552.9  783.48   572.3  783.26
#Mann= 3 , 0 , 0
       0      .1       0   143.5    .045       0   158.5     .06       0
Bank Sta=143.5,158.5
XS Rating Curve= 0 ,0
Exp/Cntr=0.3,0.1

Type RM Length L Ch R = 1 ,9921.5  ,247.8,253.2,258.6
XS GIS Cut Line= 2
     1664554.181      329545.262     1665088.621        329435.1
#Sta/Elev= 30
       0  815.63    29.2  797.13      39  792.69    48.7  790.98    58.5  790.08
      78  783.72    87.7  778.36    97.4  772.05   107.2  764.81   116.9  758.35
   126.7  755.67   127.6  755.74   136.4  756.45   142.6  757.72   146.2  758.46
   155.9  763.41   165.6   764.6   224.1  765.94   253.4  768.49   331.3  772.62
   370.3   775.1     380  776.32   389.8   778.7   428.8   791.6   438.5  797.71
     497  816.96   516.4  822.81   526.2  828.18   535.9  831.32   545.7   833.7
#Mann= 3 , 0 , 0
       0      .1       0   127.6    .045       0   142.6     .06       0
Bank Sta=127.6,142.6
XS Rating Curve= 0 ,0
Exp/Cntr=0.3,0.1

Type RM Length L Ch R = 1 ,9668.4  ,554.2,565.2,576.1
XS GIS Cut Line= 2
     1664562.818      329764.587     1664967.134      329779.982
#Sta/Elev= 30
       0  828.99     9.6  822.47    19.3  816.21    28.9  810.46    67.4  789.72
    77.1  783.85    86.7  774.52    96.3  769.39   115.6  757.22   125.2  753.98
   132.7  753.63   134.9  753.53   144.5  754.73   147.7  755.47   163.8  758.99
   173.4  760.32   202.3  761.62   231.2  763.43   260.1  764.61     289  767.78
   298.6   769.3   308.3  771.21   317.9  774.45   327.5  778.96   337.2  782.49
   346.8  784.06   356.4  788.69   366.1  795.26   385.3  805.54   404.6   816.3
#Mann= 3 , 0 , 0
       0      .1       0   132.7    .045       0   147.7     .06       0
Bank Sta=132.7,147.7
XS Rating Curve= 0 ,0
Exp/Cntr=0.3,0.1

Type RM Length L Ch R = 1 ,9103.2  ,395.9,399.7,403.6
XS GIS Cut Line= 2
     1664342.659      330203.022     1664625.606      330365.854
#Sta/Elev= 28
       0  815.26    38.4  794.86      48  790.29    57.6   787.1    67.2  783.34
    76.8  778.11    86.4  770.61      96  762.91   105.6  756.41   107.5  755.55
   115.2  752.06   122.5  751.28   124.8  751.04   134.4  751.75   163.2  755.05
     192  758.15   201.6  759.57   211.2  760.77   220.8   761.8   230.4  762.54
     240  764.03   249.6  764.83   259.2     767   268.8  771.94   278.4  777.82
   307.2  793.89   316.8   802.9   326.5   808.8
#Mann= 3 , 0 , 0
       0      .1       0   107.5    .045       0   122.5     .06       0
Bank Sta=107.5,122.5
XS Rating Curve= 0 ,0
Exp/Cntr=0.3,0.1

Type RM Length L Ch R = 1 ,8703.2  ,797.5,800.1,802.7
XS GIS Cut Line= 2
     1664064.859      330462.476     1664355.981      330704.001
#Sta/Elev= 30
       0  806.38     9.7  802.71    19.4  797.06    29.1  792.88    38.8  788.95
    67.9  776.85    77.6  772.68    87.3  768.32      97  764.72   106.7  762.08
   116.4   758.2   126.1  755.13   145.5  750.49   155.2  748.33   160.9  747.47
   164.9  746.87   174.6  746.89   175.9   747.1   184.3  748.45     194   750.9
   203.7   752.3   223.1  753.59   271.6  756.19   300.7  758.04   310.4   758.8
   320.1  760.34   329.8  764.04   349.2   773.5   368.6  782.61   378.3  785.08
#Mann= 3 , 0 , 0
       0      .1       0   160.9    .045       0   175.9     .06       0
Bank Sta=160.9,175.9
XS Rating Curve= 0 ,0
Exp/Cntr=0.3,0.1

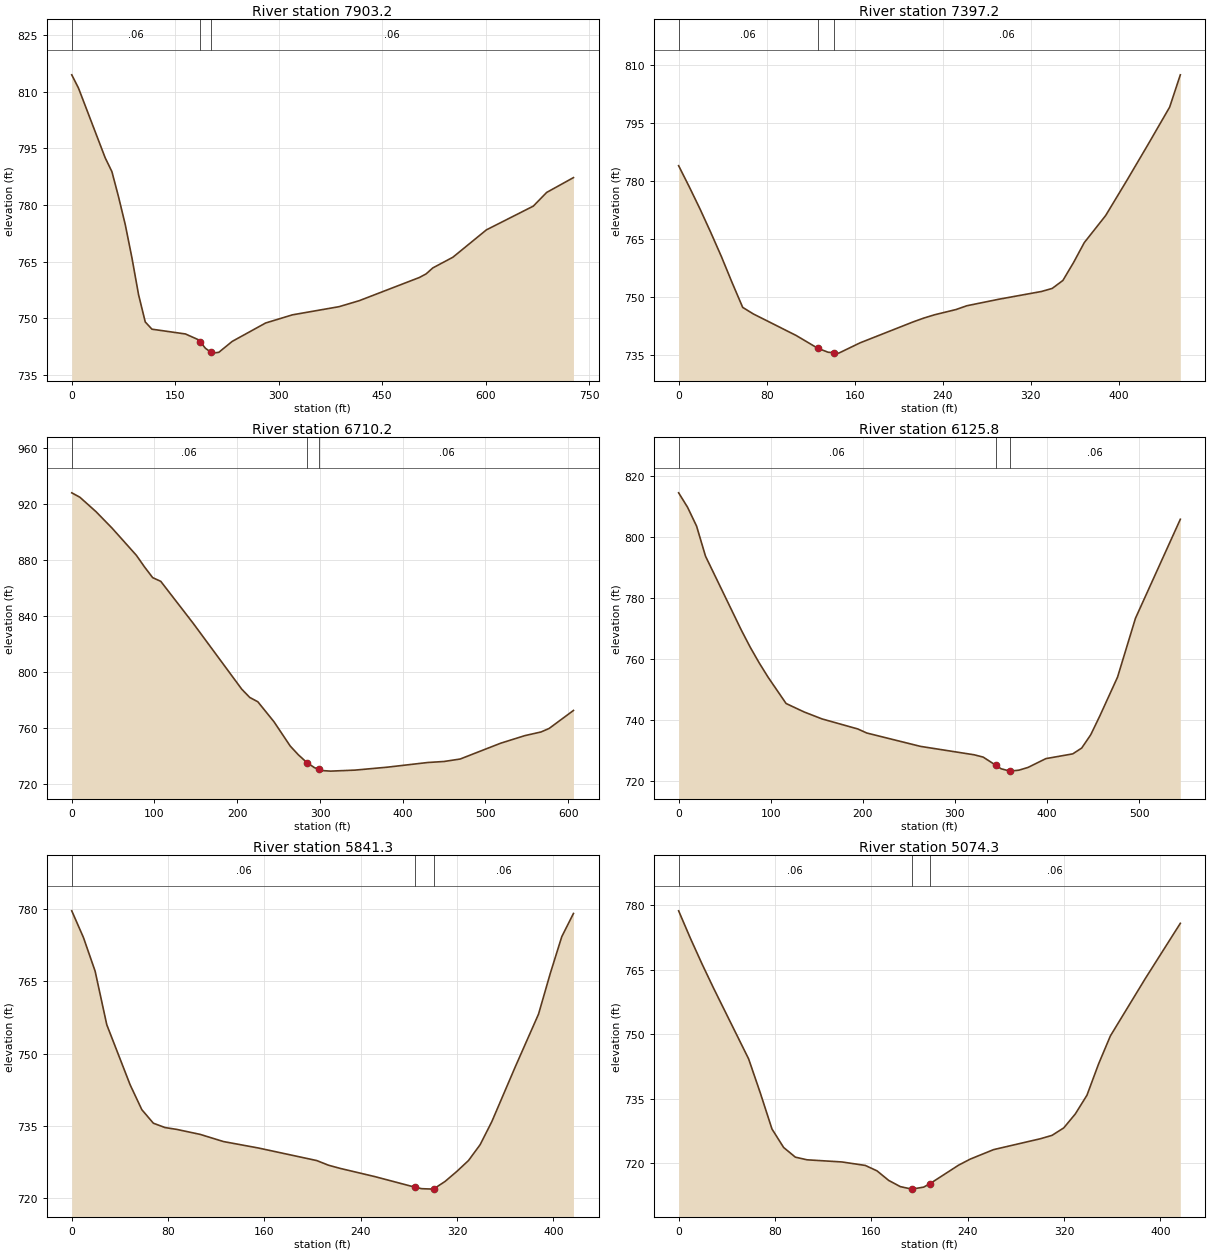
Type RM Length L Ch R = 1 ,7903.2  ,517.5,506,494.5
XS GIS Cut Line= 3
     1663428.085      330907.609     1663762.737      331258.197
      1663930.37      331433.812
#Sta/Elev= 30
       0  814.47     9.7  810.99    48.5  792.48    58.2  788.84    67.8  782.18
    77.6  774.78    87.2  766.06    96.9  756.21   106.6     749   116.3  747.09
   164.8  745.83   184.2  744.25   186.4  743.74   193.9  742.02   201.4  741.04
   203.6  740.75   213.2  740.96   232.6  743.85   281.1  748.73   319.9  750.89
   387.7  753.06   416.8  754.64   504.1  760.79   513.8  761.74   523.5  763.32
   552.6  766.15   601.2   773.4   669.2  779.69   688.6  783.32   727.4  787.24
#Mann= 3 , 0 , 0
       0     .06       0   186.4    .045       0   201.4     .06       0
Bank Sta=186.4,201.4
XS Rating Curve= 0 ,0
Exp/Cntr=0.3,0.1

Type RM Length L Ch R = 1 ,7397.2  ,673.9,686.5,699.1
XS GIS Cut Line= 2
     1663197.713      331402.203     1663633.726      331534.982
#Sta/Elev= 30
       0  783.88     9.7   778.4    19.4   772.7    29.1  766.67    38.8   760.4
    48.5  753.68    58.2  747.21    67.9  745.51   106.7  739.95   126.4  736.63
   135.8   735.6   141.4  735.47   145.5  735.37   164.9  738.04   213.3  743.48
     223  744.47   232.7  745.31   252.1  746.66   261.8  747.63   290.9  749.32
   329.7  751.33   339.4  752.12   349.1  754.18   358.8  758.83   368.5  763.96
   387.9  770.96   407.3  780.11   426.7  789.49   446.1  799.05   455.8  807.41
#Mann= 3 , 0 , 0
       0     .06       0   126.4    .045       0   141.4     .06       0
Bank Sta=126.4,141.4
XS Rating Curve= 0 ,0
Exp/Cntr=0.3,0.1

Type RM Length L Ch R = 1 ,6710.2  ,605.3,584.2,563.2
XS GIS Cut Line= 2
     1662744.285      331531.749      1663139.92      331991.127
#Sta/Elev= 30
       0  928.25     9.8  925.11    29.3  914.77    48.9  902.87    78.2  883.44
      88  875.14    97.8  867.53   107.6  864.87   146.7  834.89   205.4   787.7
   215.1  781.76   224.9  778.65   244.5  764.27     264  746.98   273.8  740.72
   284.1  735.17   293.4  731.46   299.1  730.24   303.1  729.38   312.9     729
   342.2  729.72   381.4  731.83   430.2  735.17   449.8   735.9   469.4  737.66
   518.3  748.98   547.6  754.42   567.2  757.05   576.9  759.55   606.3  772.43
#Mann= 3 , 0 , 0
       0     .06       0   284.1    .045       0   299.1     .06       0
Bank Sta=284.1,299.1
XS Rating Curve= 0 ,0
Exp/Cntr=0.3,0.1

Type RM Length L Ch R = 1 ,6125.8  ,281.7,284.7,287.6
XS GIS Cut Line= 2
     1662495.088      332325.553     1663038.025      332281.166
#Sta/Elev= 30
       0  814.37     9.7  809.65    19.5  803.47    29.2  793.64    68.1  769.44
    77.8  763.83    87.6  758.67    97.3  753.98   116.7  745.44   136.2  742.69
   155.6  740.41   194.6  737.11   204.3  735.79   262.6  731.42     321  728.66
   330.7  727.91   344.3  725.27   350.2  724.09   359.3  723.37   359.9  723.32
   369.6  723.64   379.4  724.53   398.8  727.41     428  728.97   437.7  730.87
   447.5  735.21   457.2  741.26   476.6  754.06   496.1  773.34   544.8  805.72
#Mann= 3 , 0 , 0
       0     .06       0   344.3    .045       0   359.3     .06       0
Bank Sta=344.3,359.3
XS Rating Curve= 0 ,0
Exp/Cntr=0.3,0.1

Type RM Length L Ch R = 1 ,5841.3  ,771.7,766.7,761.7
XS GIS Cut Line= 2
     1662613.122      332559.013     1663029.327      332580.103
#Sta/Elev= 30
       0  779.62     9.7   774.1    19.4  767.13    29.1  756.01    48.5  743.56
    58.2  738.41    67.8   735.6    77.5   734.7    87.2  734.32   106.6  733.29
     126   731.8   155.1  730.46   203.5  727.86   213.2   726.9   222.9  726.24
     252  724.52   285.5  722.31   290.8  722.03   300.4  721.94   300.5  721.96
   310.1  723.54   319.8   725.6   329.5  727.86   339.2  731.15   348.9  735.93
   368.3  747.24   387.7  758.21   397.4   766.6     407  774.26   416.7  779.07
#Mann= 3 , 0 , 0
       0     .06       0   285.5    .045       0   300.5     .06       0
Bank Sta=285.5,300.5
XS Rating Curve= 0 ,0
Exp/Cntr=0.3,0.1

Type RM Length L Ch R = 1 ,5074.3  ,364.1,371,377.8
XS GIS Cut Line= 2
     1662656.595      333331.611      1663067.27      333261.347
#Sta/Elev= 30
       0  778.66     9.7  772.33    19.4  766.34    29.1  760.65    58.1  744.29
    67.8  736.38    77.5     728    87.2   723.7    96.9  721.46   106.6  720.84
   135.6  720.34     155  719.53   164.7  718.28   174.4  716.06   184.1  714.61
   193.7  714.03   203.5   714.5   208.7   715.3   232.5   719.6   242.2  721.01
   261.6  723.21   300.4  725.73   310.1  726.52   319.8  728.25   329.4  731.49
   339.1  735.86   348.8  743.16   358.5   749.6   387.6  762.97   416.6  775.76
#Mann= 3 , 0 , 0
       0     .06       0   193.7    .045       0   208.7     .06       0
Bank Sta=193.7,208.7
XS Rating Curve= 0 ,0
Exp/Cntr=0.3,0.1

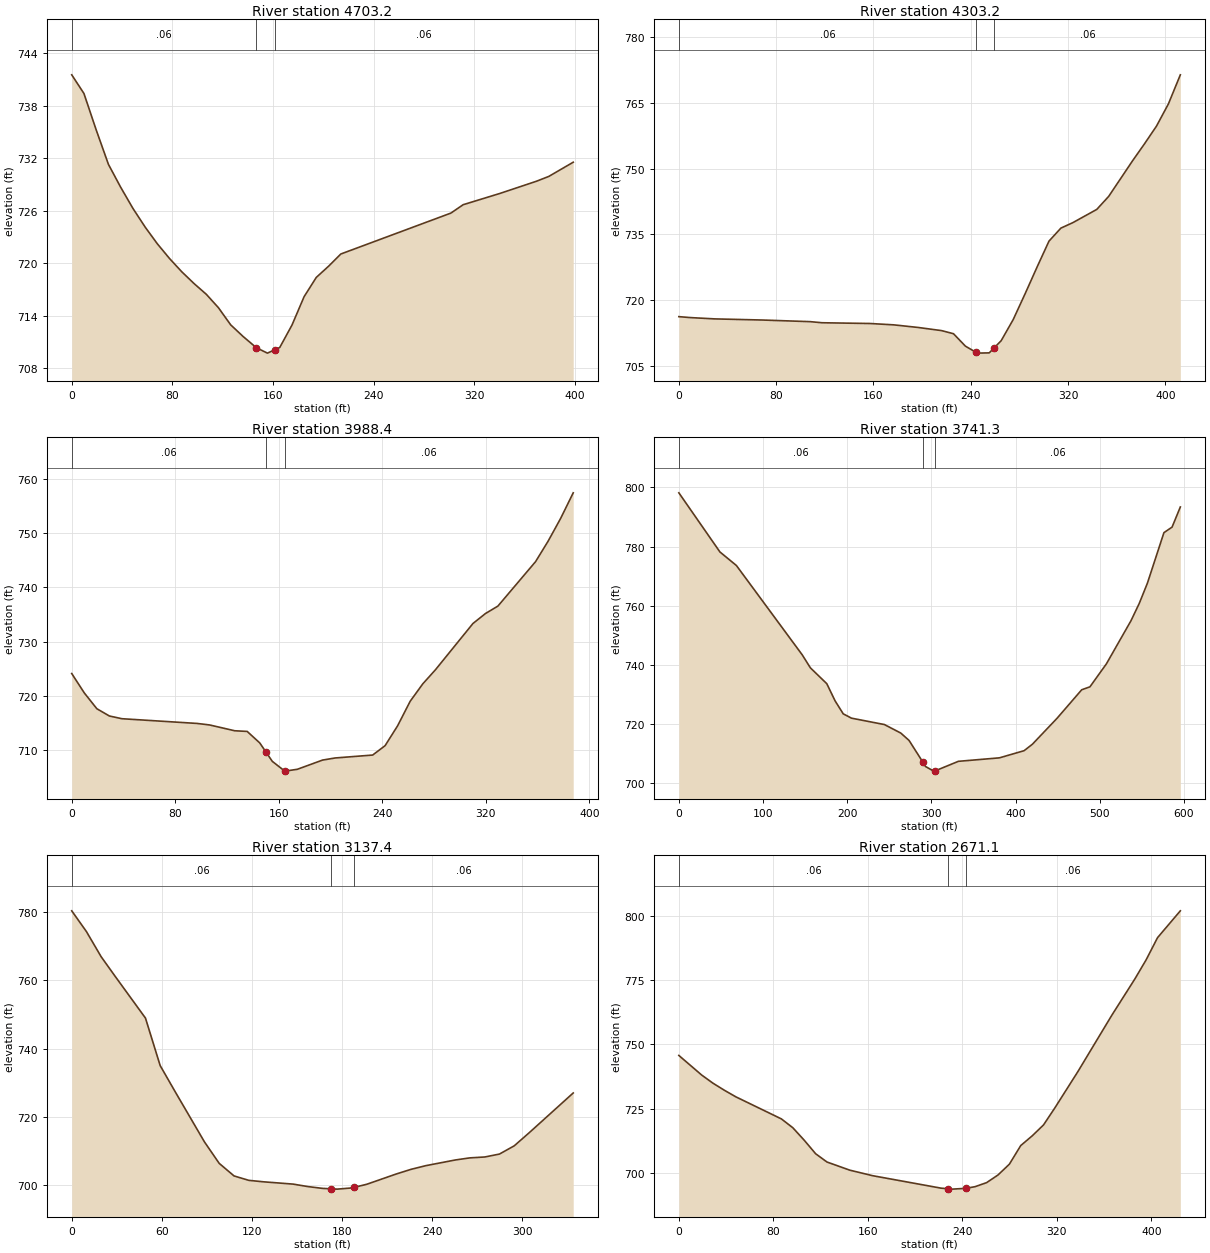
Type RM Length L Ch R = 1 ,4703.2  ,391.1,400,409.7
XS GIS Cut Line= 2
     1662744.607      333638.397     1663139.814      333691.804
#Sta/Elev= 30
       0  741.52     9.7  739.39    19.4  735.25    29.2  731.29    38.9  728.69
    48.6  726.28    58.4  724.13    68.1  722.22    77.8  720.54    87.5  719.03
    97.3  717.68     107  716.46   116.7  714.92   126.4  712.97   136.2  711.65
   146.8  710.36   155.6  709.74   161.8  710.14   165.4  710.38   175.1  712.93
   184.8  716.19   194.5  718.39   204.3  719.67     214  721.06   301.5  725.73
   311.3  726.69   340.4  727.97   369.6  729.37   379.4  729.92   398.8  731.54
#Mann= 3 , 0 , 0
       0     .06       0   146.8    .045       0   161.8     .06       0
Bank Sta=146.8,161.8
XS Rating Curve= 0 ,0
Exp/Cntr=0.3,0.1

Type RM Length L Ch R = 1 ,4303.2  ,302,314.8,326.7
XS GIS Cut Line= 2
     1662707.016      333907.799     1663053.734      334130.886
#Sta/Elev= 30
       0  716.25     9.8  716.03    29.4  715.74    68.7  715.48     108  715.11
   117.8  714.86   157.1  714.69   176.7  714.38   196.3   713.8     216  713.07
   225.8  712.36   235.6  709.53   244.5  708.09   245.4  707.94   255.2     708
   259.5  709.22     265  710.77   274.9  715.59   284.7  721.48   294.5  727.54
   304.3  733.45   314.1  736.42   323.9  737.66   343.6  740.68   353.4  743.65
     373  751.75   382.8  755.61   392.7  759.66   402.5  764.72   412.3  771.34
#Mann= 3 , 0 , 0
       0     .06       0   244.5    .045       0   259.5     .06       0
Bank Sta=244.5,259.5
XS Rating Curve= 0 ,0
Exp/Cntr=0.3,0.1

Type RM Length L Ch R = 1 ,3988.4  ,250.5,247,243.6
XS GIS Cut Line= 2
        1662552.      334010.973      1662731.51      334354.475
#Sta/Elev= 30
       0  724.14     9.7  720.57    19.4  717.66    29.1  716.32    38.8  715.82
    96.9  714.95   106.6  714.67     126   713.6   135.6  713.48   145.3  711.37
   150.1  709.69     155  707.97   164.7  706.17   165.1  706.18   174.4  706.51
   193.8   708.2   203.5  708.59   232.6  709.13   242.2  710.86   251.9  714.53
   261.6  719.04   271.3  722.23     281   724.8   310.1  733.35   319.8  735.19
   329.4  736.56   358.5  744.74   368.2  748.51   377.9  752.71   387.6  757.41
#Mann= 3 , 0 , 0
       0     .06       0   150.1    .045       0   165.1     .06       0
Bank Sta=150.1,165.1
XS Rating Curve= 0 ,0
Exp/Cntr=0.3,0.1

Type RM Length L Ch R = 1 ,3741.3  ,620.7,603.9,587.1
XS GIS Cut Line= 2
     1662254.794      334051.502     1662605.647      334533.034
#Sta/Elev= 30
       0  798.14    48.8  778.16    68.4  773.57   146.5  743.42   156.3  738.99
   175.8  733.63   185.6  727.84   195.3  723.45   205.1  721.99   244.2  719.83
   263.7  716.95   273.5  714.46   289.7  707.22     293  705.66   302.8  704.09
   304.7   704.2   332.1   707.4   380.9  708.58   410.2     711     420  713.17
   449.3  721.94   478.6  731.58   488.4  732.58   507.9  740.32   537.2  754.93
     547  760.77   556.7  767.63   576.3  784.68     586  786.56   595.8  793.36
#Mann= 3 , 0 , 0
       0     .06       0   289.7    .045       0   304.7     .06       0
Bank Sta=289.7,304.7
XS Rating Curve= 0 ,0
Exp/Cntr=0.3,0.1

Type RM Length L Ch R = 1 ,3137.4  ,458.8,466.4,473.9
XS GIS Cut Line= 2
     1661893.269      334622.268     1662219.947       334691.87
#Sta/Elev= 30
       0  780.27     9.8  774.19    19.6  766.84    29.5  760.76    49.1  748.91
    58.9  735.01    68.8  727.43    88.4  712.69    98.2  706.42   108.1  702.74
   117.9  701.45   127.7  701.02   147.4  700.35   157.2  699.63     167   699.1
   172.8  698.97   176.8  698.88   186.6  699.23   187.8  699.36   196.5   700.3
   216.1   703.3     226  704.67   235.8  705.74   255.4   707.4   265.2  708.02
   275.1  708.28   284.9  709.14   294.7  711.54   304.5   715.3     334     727
#Mann= 3 , 0 , 0
       0     .06       0   172.8    .045       0   187.8     .06       0
Bank Sta=172.8,187.8
XS Rating Curve= 0 ,0
Exp/Cntr=0.3,0.1

Type RM Length L Ch R = 1 ,2671.1  ,459.9,462.9,466
XS GIS Cut Line= 2
     1661675.837      334947.426     1662038.243      335168.459
#Sta/Elev= 30
       0  745.72    19.3  738.12    28.9  734.94    38.6  732.18    48.2  729.66
    86.8  721.08    96.5  717.64   106.1  712.82   115.8  707.55   125.4  704.34
   144.7  701.18     164  699.04   221.9   694.2   227.9  693.96   231.5  693.82
   242.9  694.12   250.8  694.78   260.5  696.34   270.1  699.29   279.8  703.51
   289.4  710.73   299.1   714.5   308.7  718.75   318.4  725.44   337.7  739.39
   366.6   761.4   385.9  775.33   395.6  782.88   405.2  791.44   424.5  801.86
#Mann= 3 , 0 , 0
       0     .06       0   227.9    .045       0   242.9     .06       0
Bank Sta=227.9,242.9
XS Rating Curve= 0 ,0
Exp/Cntr=0.3,0.1

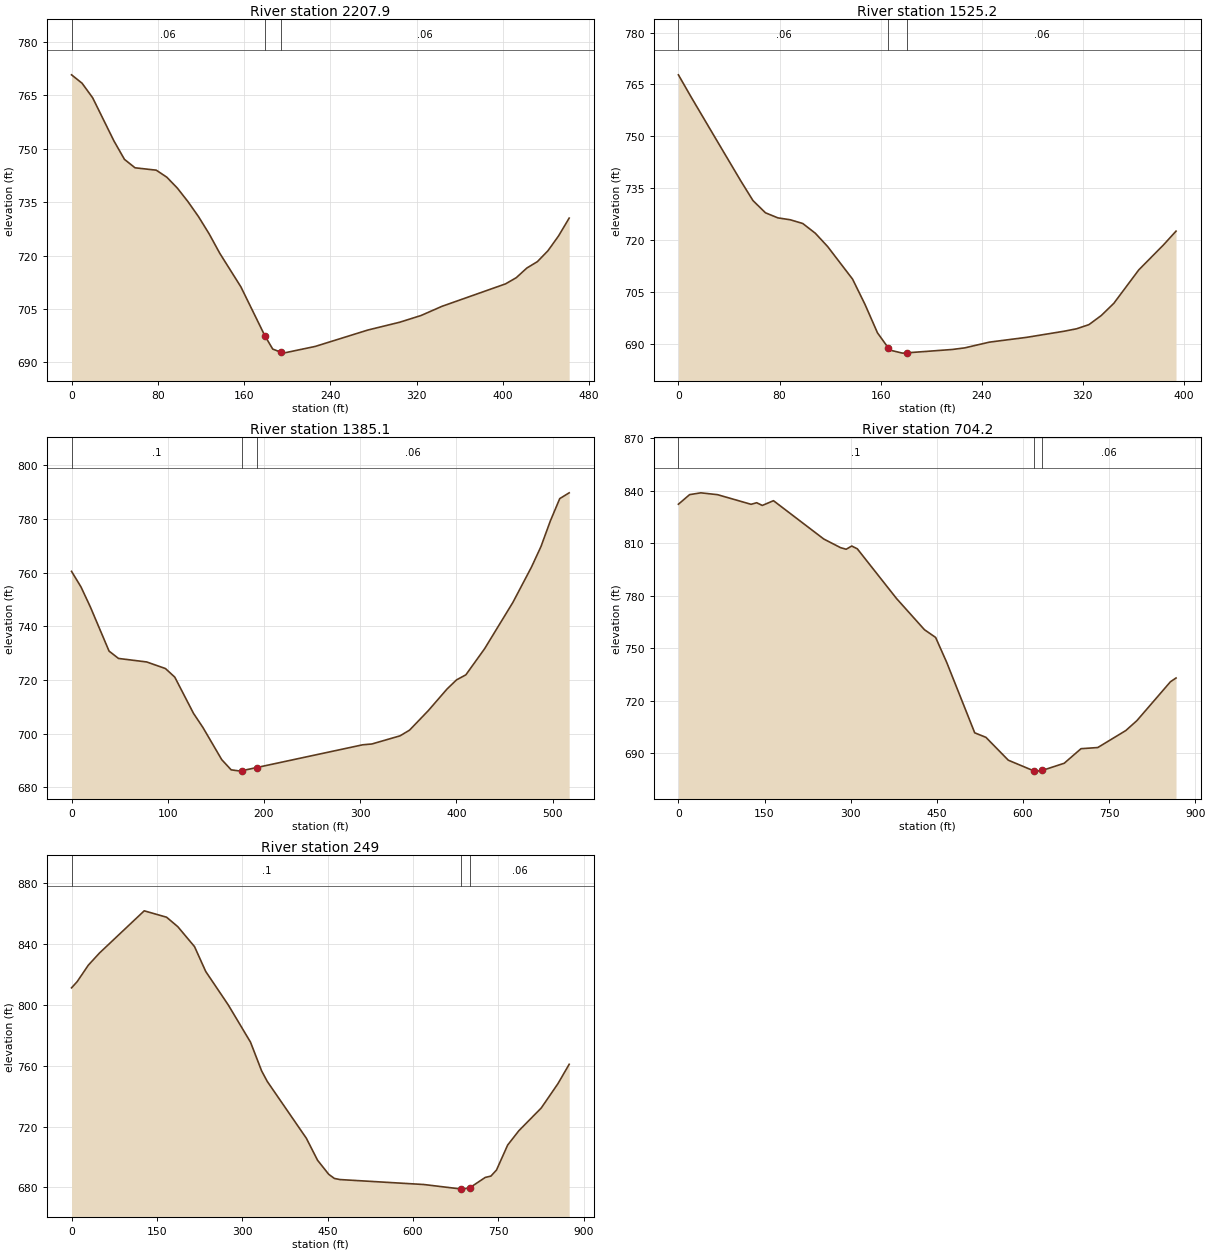
Type RM Length L Ch R = 1 ,2207.9  ,684.7,682.6,680.5
XS GIS Cut Line= 2
     1661422.359      335294.471     1661780.432      335585.738
#Sta/Elev= 30
       0   770.8     9.8  768.43    19.6  764.34    39.3  752.24    49.1  747.04
    58.9  744.68    78.6  744.01    88.4  742.03    98.2  738.96     108  735.17
   117.8  730.95   127.7  726.09   137.5  720.66   157.1  711.22   179.3   697.5
   186.6  693.75   194.3  692.85   196.4  692.61   225.9  694.48     275  699.11
   304.4  701.29   324.1  703.17   343.7  705.77   402.6  712.07   412.5   713.8
   422.3  716.51   432.1  718.31   441.9  721.37   451.8  725.56   461.6  730.55
#Mann= 3 , 0 , 0
       0     .06       0   179.3    .045       0   194.3     .06       0
Bank Sta=179.3,194.3
XS Rating Curve= 0 ,0
Exp/Cntr=0.3,0.1

Type RM Length L Ch R = 1 ,1525.2  ,132.5,140,147.6
XS GIS Cut Line= 2
     1660971.957      335771.829     1661299.262      335990.609
#Sta/Elev= 30
       0  767.78     9.8  761.53    29.5  749.34    49.2   737.2      59  731.41
    68.9  727.87    78.7  726.41    88.6  725.85    98.4  724.78   108.3  721.97
   118.1   718.1   137.8  708.69   147.6   701.4   157.5  693.16   166.1  688.78
   167.3  688.17   177.2  687.29   181.1  687.38   216.5  688.34   226.4   688.8
   246.1  690.47   275.6  691.86   305.1  693.62     315  694.33   324.8  695.53
   334.6  698.18   344.5   701.7   364.2  711.35   383.8   718.6   393.7  722.57
#Mann= 3 , 0 , 0
       0     .06       0   166.1    .045       0   181.1     .06       0
Bank Sta=166.1,181.1
XS Rating Curve= 0 ,0
Exp/Cntr=0.3,0.1

Type RM Length L Ch R = 1 ,1385.1  ,686.3,680.8,675.3
XS GIS Cut Line= 2
     1660912.771      335823.208     1661222.315       336237.48
#Sta/Elev= 30
       0  760.49     9.8   754.7    19.5  747.27      39  730.76    48.8  728.03
    78.1  726.72    97.6  724.26   107.3  721.06   126.8  707.53   136.6  702.26
   156.1   690.3   165.9   686.5   175.6  686.02   177.5  686.21   192.5  687.36
   302.5  695.83   312.2  696.14   341.5  699.19   351.3   701.3   370.8  708.58
   390.3  716.65   400.1  720.03   409.8  721.91   429.3  731.65   458.6  748.86
   478.1  762.15   487.9  769.76   497.6  779.26   507.4  787.62   517.2  789.77
#Mann= 3 , 0 , 0
       0      .1       0   177.5    .045       0   192.5     .06       0
Bank Sta=177.5,192.5
XS Rating Curve= 0 ,0
Exp/Cntr=0.3,0.1

Type RM Length L Ch R = 1 ,704.2   ,463.2,454,444.7
XS GIS Cut Line= 2
      1659954.54      335881.136     1660630.381      336423.734
#Sta/Elev= 30
       0  832.24    19.5  837.73      39  838.76    68.2   837.7   126.6   832.2
   136.3   833.1   146.1  831.55   165.6  834.26   253.2  812.36   282.4  807.43
   292.2  806.52   301.9  808.37   311.6  806.77   379.8   778.4   428.5  760.56
     448  756.12   467.4  741.79   516.1  701.61   535.6  699.04   574.6  685.97
   618.7  679.92   623.2  679.73   633.7  680.13   671.9  684.22   701.2  692.55
   730.4  693.21   779.1  702.89   798.5  708.57     857  730.81   866.7  732.95
#Mann= 3 , 0 , 0
       0      .1       0   618.7    .045       0   633.7     .06       0
Bank Sta=618.7,633.7
XS Rating Curve= 0 ,0
Exp/Cntr=0.3,0.1

Type RM Length L Ch R = 1 ,249     ,261.5,249.9,238.2
XS GIS Cut Line= 2
     1659535.305      336442.939      1660369.46      336705.107
#Sta/Elev= 30
       0   811.2     9.8  815.25    29.5  826.11    49.1   834.1   127.7  861.82
     167  857.62   186.7   851.4   216.1   838.3   235.8  821.95   275.1  800.14
   314.4  775.57     334  756.62   343.9  749.71   412.6  712.35   432.3   697.9
   451.9  688.67   461.8  685.96   471.6  685.22     619  681.96     685  678.99
   687.7  678.93     700   679.9     727  686.63   736.8  687.47   746.7  691.48
   766.3  707.89     786  717.32   825.3  732.24   854.7  748.26   874.4  760.96
#Mann= 3 , 0 , 0
       0      .1       0     685    .045       0     700     .06       0
Bank Sta=685,700
XS Rating Curve= 0 ,0
Exp/Cntr=0.3,0.1

Chan Stop Cuts=-1
Use User Specified Reach Order=0
Composite Channel Slope=5